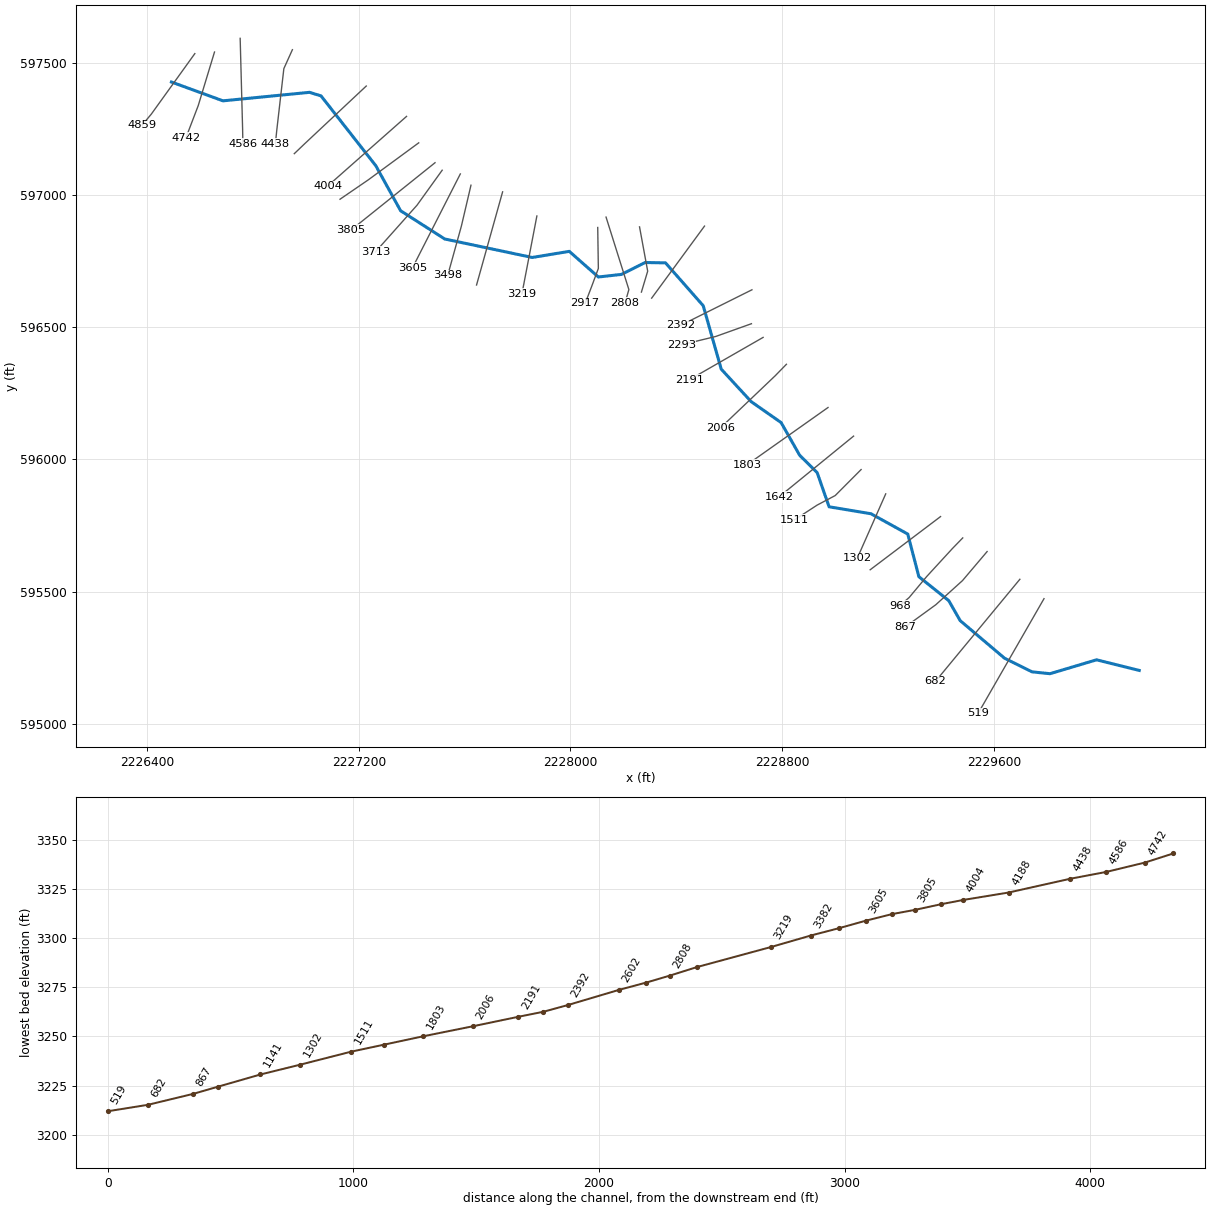
--- POTATOHFK.prj (project) ---

Proj Title=POTATOHFK
Current Plan=p01
Default Exp/Contr=0,0
English Units
Geom File=g01
Flow File=f01
Plan File=p01
BEGIN DESCRIPTION:
----------MODEL BY WOOD PLC 2022----------
AFH study
Randolph County, WV
HEC-RAS Version: RAS 6.2
Vertical Datum: NAVD88
Projection: NAD 1983 StatePlane West Virginia S FIPS 4702 (US Feet)
Terrain: 1-meter LIDAR (FEMA Region III 3DEP collected 2016-2018)
Land Use: 2019 NLCD
Hydrologic Method:
WV SIR2010-5033 regression equations
Additional Model Notes:
Main stem is MILLCK
END DESCRIPTION:
DSS Export Rating Curves= 0
DSS Export Rating Curve Sorted= 0
DSS Export Volume Flow Curves= 0
DXF OffsetX= 0
DXF OffsetY= 0
DXF ScaleX= 0
DXF ScaleY= 0

--- POTATOHFK.p01 (plan) ---

Plan Title=Floodplain
Program Version=6.20
Short Identifier=Floodplain
Geom File=g01
Flow File=f01
Subcritical Flow
K Sum by GR= 0
Std Step Tol= 0.01
Critical Tol= 0.01
Num of Std Step Trials= 20
Max Error Tol= 0.3
Flow Tol Ratio= 0.001
Split Flow NTrial= 30
Split Flow Tol= 0.02
Split Flow Ratio= 0.02
Log Output Level= 0
Friction Slope Method= 1
Unsteady Friction Slope Method= 2
Unsteady Bridges Friction Slope Method= 1
Parabolic Critical Depth
Global Vel Dist= 0 , 0 , 0
Global Log Level= 0
CheckData=True
Encroach Param=-1 ,0,0, 0
Mapping Interval=1HOUR
Computation Time Step Use Courant=        0
Computation Time Step Use Time Series=    0
Computation Time Step Count To Double=0
Computation Time Step Max Doubling=0
Computation Time Step Max Halving=0
Computation Time Step Residence Courant=0
Run HTab= 0
Run UNet= 0
Run Sediment= 0
Run PostProcess= 0
Run WQNet= 0
Run RASMapper=-1
UNET Theta= 0
UNET Theta Warmup= 0
UNET ZTol= 0
UNET ZSATol= 0
UNET MxIter= 0
UNET Max Iter WO Improvement= 0
UNET MaxInSteps= 0
UNET DtIC= 0
UNET DtMin= 0
UNET MaxCRTS= 0
UNET WFStab= 0
UNET SFStab= 0
UNET WFX= 1
UNET SFX= 1
UNET Gravity=32.174
UNET 1D Methodology=Finite Difference
UNET DSS MLevel= 1
UNET Pardiso=0
UNET DZMax Abort= 0
UNET Use Existing IB Tables= 0
UNET Froude Reduction=False
UNET Froude Limit= 0
UNET Froude Power= 0
UNET D1 Cores= 0
UNET WindReference=Eulerian
UNET WindDragFormulation=Hsu (1988)
UNET D2 Coriolis=0
UNET D2 Cores= 0
UNET D2 Theta= 1
UNET D2 Theta Warmup= 1
UNET D2 Z Tol= 0.01
UNET D2 Volume Tol= 0.01
UNET D2 Max Iterations= 20
UNET D2 Equation= 0
UNET D2 RampUpFraction=0.1
UNET D2 TimeSlices= 1
UNET D2 Turbulence Formulation=Non-Conservative (original)
UNET D2 Eddy Viscosity=0.3
UNET D2 Transverse Eddy Viscosity=0.1
UNET D2 Smagorinsky Mixing=0
UNET D2 BCVolumeCheck=0
UNET D2 Cores=0
UNET D2 SolverType=PARDISO (Direct)
UNET D2 Minimum Iterations= 2147483647
UNET D2 Maximum Iterations= 2147483647
UNET D2 Restart Number= 10
UNET D2 Relaxation Coeff=1.3
UNET D2 SOR Precondition Iterations= 10
UNET D2 ILUT Maximum Fill= 8
UNET D2 ILUT Tolerance=1E-08
UNET D1D2 MaxIter= 0
UNET D1D2 ZTol=0.01
UNET D1D2 QTol=0.1
UNET D1D2 MinQTol=1
Write IC File= 0
Write IC File at Fixed DateTime=0
Write IC File at Sim End=0
Echo Input=False
Echo Parameters=False
Echo Output=False
Write Detailed= 0
HDF Write Warmup=0
HDF Write Time Slices=0
HDF Flush=0
HDF Compression= 1
HDF Chunk Size= 1
HDF Spatial Parts= 1
HDF Use Max Rows=0
HDF Fixed Rows= 1
Calibration Method= 0
Calibration Iterations= 20
Calibration Max Change=0.05
Calibration Tolerance=0.2
Calibration Maximum=1.5
Calibration Minimum=0.5
Calibration Optimization Method= 1
WQ AD Non Conservative
WQ ULTIMATE=-1
WQ Max Comp Step=1HOUR
WQ Output Interval=15MIN
WQ Output Selected Increments= 0
WQ Output face flow=0
WQ Output face velocity=0
WQ Output face area=0
WQ Output face dispersion=0
WQ Output cell volume=0
WQ Output cell surface area=0
WQ Output cell continuity=0
WQ Output cumulative cell continuity=0
WQ Output face conc=0
WQ Output face dconc_dx=0
WQ Output face courant=0
WQ Output face peclet=0
WQ Output face adv mass=0
WQ Output face disp mass=0
WQ Output cell mass=0
WQ Output cell source sink temp=0
WQ Output nsm pathways=0
WQ Output nsm derived pathways=0
WQ Create Restart=0
WQ Fixed Restart=0
WQ System Summary=0
WQ Write To DSS=0
Sorting and Armoring Iterations= 10
XS Update Threshold= 0.02
Bed Roughness Predictor= 0
Hydraulics Update Threshold= 0.02
Energy Slope Method= 1
Volume Change Method= 1
Sediment Retention Method= 0
Sediment TS Multiplier= 1
Warm Up Method= 0
XS Weighting Method= 0
Number of US Weighted Cross Sections= 1
Number of DS Weighted Cross Sections= 1
Upstream XS Weight=0
Main XS Weight=1
Downstream XS Weight=0
Number of DS XS's Weighted with US Boundary= 1
Upstream Boundary Weight= 1
Weight of XSs Associated with US Boundary= 0
Number of US XS's Weighted with DS Boundary= 1
Downstream Boundary Weight= 0.5
Weight of XSs Associated with DS Boundary= 0.5
Percentile Method= 0
Sediment Output Level= 3
Mass or Volume Output= 0
Output Increment Type= 1
Profile and TS Output Increment= 1
Transport Output Increment 1
XS Output Flag= 0
XS Output Increment= 10
Read HDF5 Sediment Hotstart= 0
Sediment Hotstart Type= 0
Write Gradation File= 0
Read Gradation Hotstart= 0
Write HDF5 File= 1
Write Binary Output= 1
Write DSS Sediment File= 0
DSS Sediment Output Type= 1
SV Curve= 0
Specific Gage Flag= 0
Subcell Erosion Methods= 0
Subcell Deposition Methods= 0
Advection Scheme= 1
Matrix Solver= 0
Implicit Weighting Factor= 1
Maximum Outer Loop Convergence Iterations= 5
Convergence Maximum Absolute= 0.001
Convergence RMSE= 0.0001
Grain Fractions Max Abs Error= 0.001
Max Subgrid Regions= 1
Max Subgrid Length Scale= 3.402823E+38
Initial Layer Thickness= 3.402823E+38
Min Layer Thickness= 3.402823E+38
Max Layer Thickness= 3.402823E+38
Number of Layers= 5

--- POTATOHFK.f01 (steady flow) ---

Flow Title=Flow
Program Version=6.20
Number of Profiles= 1
Profile Names=P100yr
River Rch & RM=POTATOHFK,Main,4859
     462
Boundary for River Rch & Prof#=POTATOHFK,Main            , 1
Up Type= 0
Dn Type= 3
Dn Slope=0.034251
DSS Import GetInterval= 0
DSS Import GetPeak= 0
DSS Import FillOption= 0

--- POTATOHFK.g01 (geometry) ---

Geom Title=Geometry
Program Version=6.20

River Reach=POTATOHFK       ,Main
Reach XY= 30
2226491.53200001597426.6070000082226686.40999998597355.427000001
     2227013.552 597387.598000022227057.06999999597374.090000004
     2227264.101 597110.201000022227357.85100001596940.062000021
2227524.51800001596833.2919999962227855.24700002596763.413000003
2227995.35499999596786.5139999992228105.24699999596689.628000021
2228192.83104805596699.4007393712228281.89600001      596744.316
     2228359.153596743.0139999992228501.68800001596580.948000014
     2228569.743596341.3640000082228682.93799999596218.447999999
2228796.13200003596139.281000003     2228866.271596015.670000017
2228932.28399999595950.2610000072228977.46900003595820.965000018
2229135.84900001595794.7020000072229274.79500002595718.013999999
2229316.78500001595556.726000011      2229429.88 595466.00500001
2229472.94400004595390.6990000012229640.89800002595248.457000002
2229744.64500003595197.1229999962229812.35300003595190.178000018
2229988.34100004595242.617000014     2230149.761      595202.499

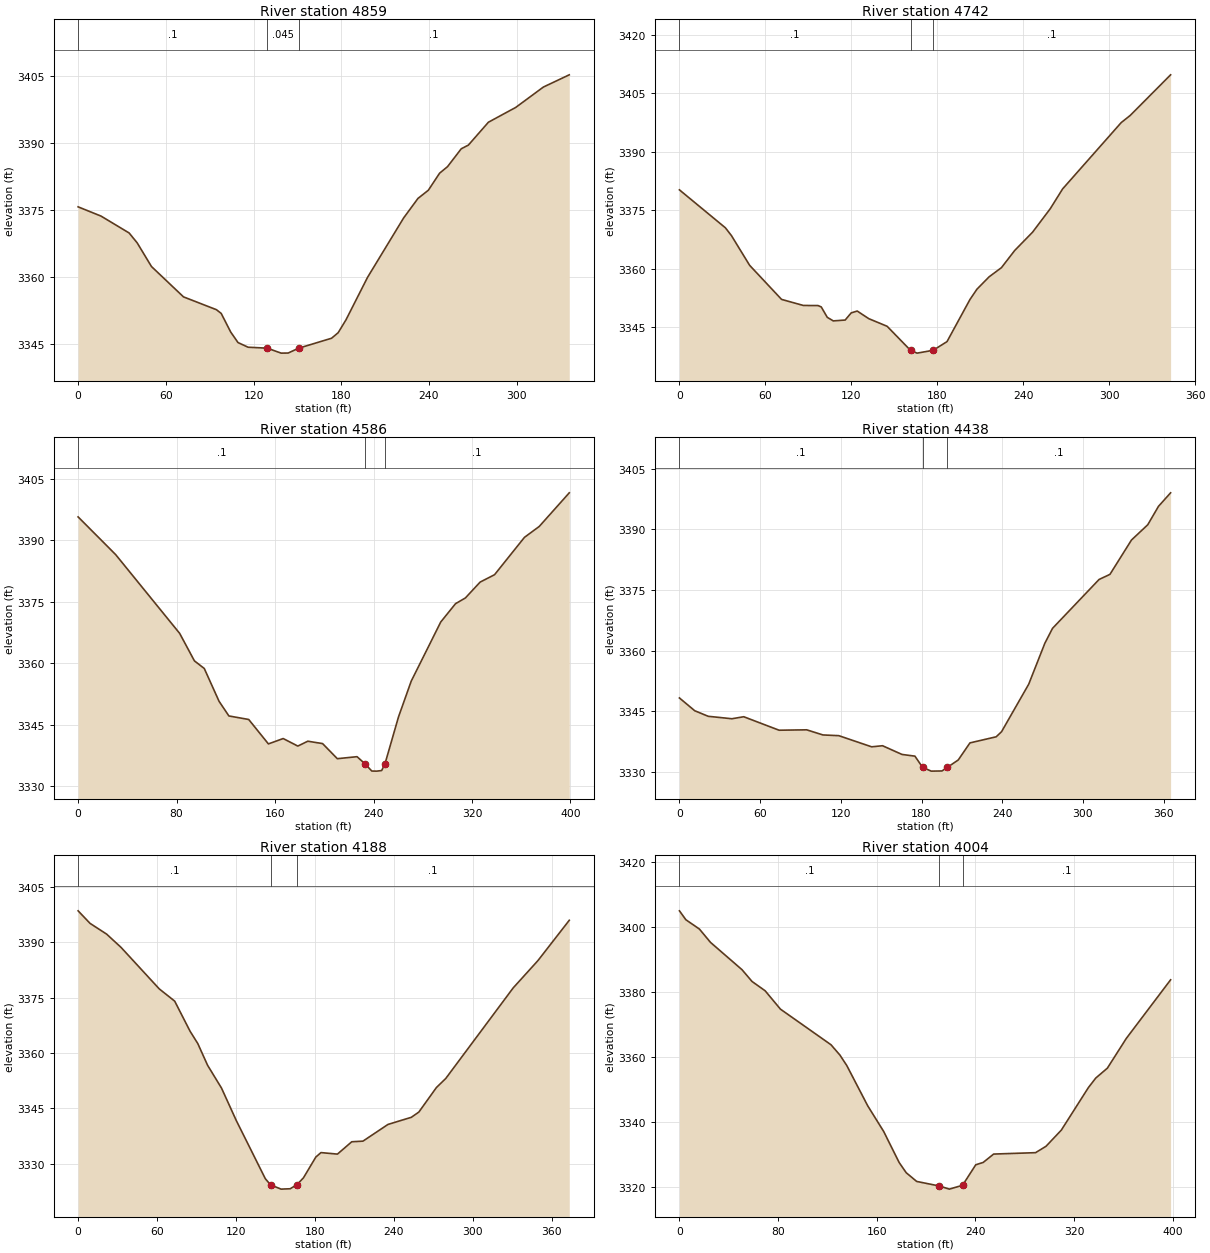
Type RM Length L Ch R = 1 ,4859    ,112.3,116.9,119.1
XS GIS Cut Line= 3
2226580.06110903597533.9376888772226415.48152288597305.131922755
2226380.69234206597263.652514862
#Sta/Elev= 30
       0 3375.73    15.7 3373.66    34.9 3369.89    40.4 3367.69    50.2 3362.39
    72.1 3355.61    94.6 3352.75    97.9 3351.91   104.4 3347.75   109.4  3345.4
   116.3 3344.36   129.4 3344.15   138.9 3343.04   143.7 3343.06  150.79 3344.13
   173.4 3346.37   177.9  3347.6   183.2 3350.44     198 3359.97   222.7 3373.25
   232.5 3377.61   239.6 3379.44   247.3 3383.25   252.7  3384.7   262.1  3388.7
     267 3389.53   280.7 3394.64   299.4 3397.95   318.3  3402.5     336 3405.23
#Mann= 3 ,0,0
       0      .1       0   129.4    .045       0  150.79      .1       0
Bank Sta=129.4,150.79
XS Rating Curve= 0 ,0
Exp/Cntr(USF)=0,0
Exp/Cntr=0.3,0.1

Type RM Length L Ch R = 1 ,4742    ,153.2,156.2,158.4
XS GIS Cut Line= 3
2226654.40338298597539.9106679212226592.98709839597337.598201034
2226546.02170429597214.765631852
#Sta/Elev= 30
       0 3380.21    32.1 3370.48    36.3 3368.49      49 3360.87    71.3 3352.13
    86.5 3350.58    96.8 3350.55      99  3350.2   103.2 3347.54   107.4 3346.62
   115.7 3346.84   119.9 3348.67   124.1 3349.15   132.2 3347.19     145 3345.24
  161.31 3339.08   165.9 3338.36   177.1 3339.08   186.8 3341.31   202.8 3352.09
   207.7 3354.75   216.2 3357.92   224.8 3360.27   234.1 3364.69   246.5 3369.35
   258.9 3375.39   267.5 3380.45   308.4 3397.45   314.7 3399.29   342.9  3409.7
#Mann= 3 ,0,0
       0      .1       0  161.31    .045       0   177.1      .1       0
Bank Sta=161.31,177.1
XS Rating Curve= 0 ,0
Exp/Cntr(USF)=0,0
Exp/Cntr=0.3,0.1

Type RM Length L Ch R = 1 ,4586    ,149.9,148,147.1
XS GIS Cut Line= 3
2226751.42113598597591.6815761872226760.69724018597247.595969871
2226761.60577796597192.820830459
#Sta/Elev= 30
       0 3395.76    30.5 3386.55    82.5  3367.3    94.5 3360.58   102.5 3358.72
   114.5 3350.71   122.5 3347.12   138.6 3346.26   154.6 3340.29   166.6  3341.6
   178.5 3339.76   186.6 3340.95   198.6 3340.37   210.6 3336.68   226.6 3337.17
   232.83335.497   238.6 3333.66   242.6 3333.64   246.6 3333.78   249.33335.433
   260.3  3346.9   270.6 3355.62   294.6 3370.08   306.6 3374.55   314.6 3375.95
   326.6 3379.83   338.3 3381.63   362.6 3390.76   374.6 3393.42     399 3401.64
#Mann= 3 ,-1,0
       0      .1       0   232.8    .045       0   249.3      .1       0
Bank Sta=232.8,249.3
XS Rating Curve= 0 ,0
Exp/Cntr(USF)=0,0
Exp/Cntr=0.3,0.1

Type RM Length L Ch R = 1 ,4438    ,256.9,250.2,243.3
XS GIS Cut Line= 4
2226948.84986061597548.7040440512226916.55798625597477.232095041
2226889.79707794597244.4121926712226884.44489627597192.228421451
#Sta/Elev= 30
       0 3348.25    11.4 3345.08    21.4 3343.71      39  3343.1    47.8  3343.6
    74.1 3340.26    94.6 3340.36   106.7 3339.09   118.5 3338.91   142.9 3336.15
     151 3336.42   165.5 3334.26   175.1 3333.84  180.74 3331.08   187.2 3330.13
   195.2 3330.17   199.3 3331.09   207.3 3332.89     216 3337.12   235.5 3338.63
   239.5 3339.89   259.7 3351.66   271.7  3361.8   277.4 3365.49     312 3377.59
   320.1 3378.86   336.1 3387.36   348.2 3391.14   356.2 3395.71   365.2 3399.05
#Mann= 3 ,0,0
       0      .1       0  180.74    .045       0   199.3      .1       0
Bank Sta=180.74,199.3
XS Rating Curve= 0 ,0
Exp/Cntr(USF)=0,0
Exp/Cntr=0.3,0.1

Type RM Length L Ch R = 1 ,4188    ,185.1,184,184.3
XS GIS Cut Line= 3
2227228.00876871 597411.402847822226993.85082093 597191.96339961
2226956.00207711597155.774652325
#Sta/Elev= 30
       0 3398.49     9.1 3395.09    21.7 3392.18    32.7 3388.57    61.7 3377.35
    73.4 3374.05    85.1  3365.9      91 3362.54    98.4 3356.69     109  3350.5
   120.2 3341.74   142.3 3325.97   146.33324.297   154.3 3323.15   161.2 3323.25
   166.43324.374   171.3 3326.22   180.7 3331.84   184.6 3333.04   197.1 3332.63
     208 3335.97   216.5 3336.14   235.5 3340.66   253.3  3342.6     259 3344.02
   272.3 3350.64   279.4 3353.09   330.7 3377.63   349.5 3385.02   373.3 3395.93
#Mann= 3 ,-1,0
       0      .1       0   146.3    .045       0   166.4      .1       0
Bank Sta=146.3,166.4
XS Rating Curve= 0 ,0
Exp/Cntr(USF)=0,0
Exp/Cntr=0.3,0.1

Type RM Length L Ch R = 1 ,4004    ,90.4,89.4,88.2
XS GIS Cut Line= 2
2227380.29749093597296.6425159662227081.69947473597033.001016957
#Sta/Elev= 30
       0 3404.88     5.2 3402.15    16.2 3399.28    25.2 3395.18    50.7 3386.81
    58.9 3383.17    69.5 3380.32    81.9 3374.68   122.9 3363.74   130.1 3360.59
   135.7 3357.36   152.7 3344.97   165.6 3337.12   178.2 3327.55   183.9 3324.43
   192.4 3321.75   210.7 3320.36   218.9 3319.39   229.6 3320.58   240.3 3326.87
   246.3 3327.59   254.8 3330.16   288.8 3330.59   297.3 3332.56   309.7 3337.53
   331.6 3350.56   337.6 3353.51     347 3356.54   362.4  3365.7   398.3 3383.69
#Mann= 3 ,-1,0
       0      .1       0   210.7    .045       0   229.6      .1       0
Bank Sta=210.7,229.6
XS Rating Curve= 0 ,0
Exp/Cntr(USF)=0,0
Exp/Cntr=0.3,0.1

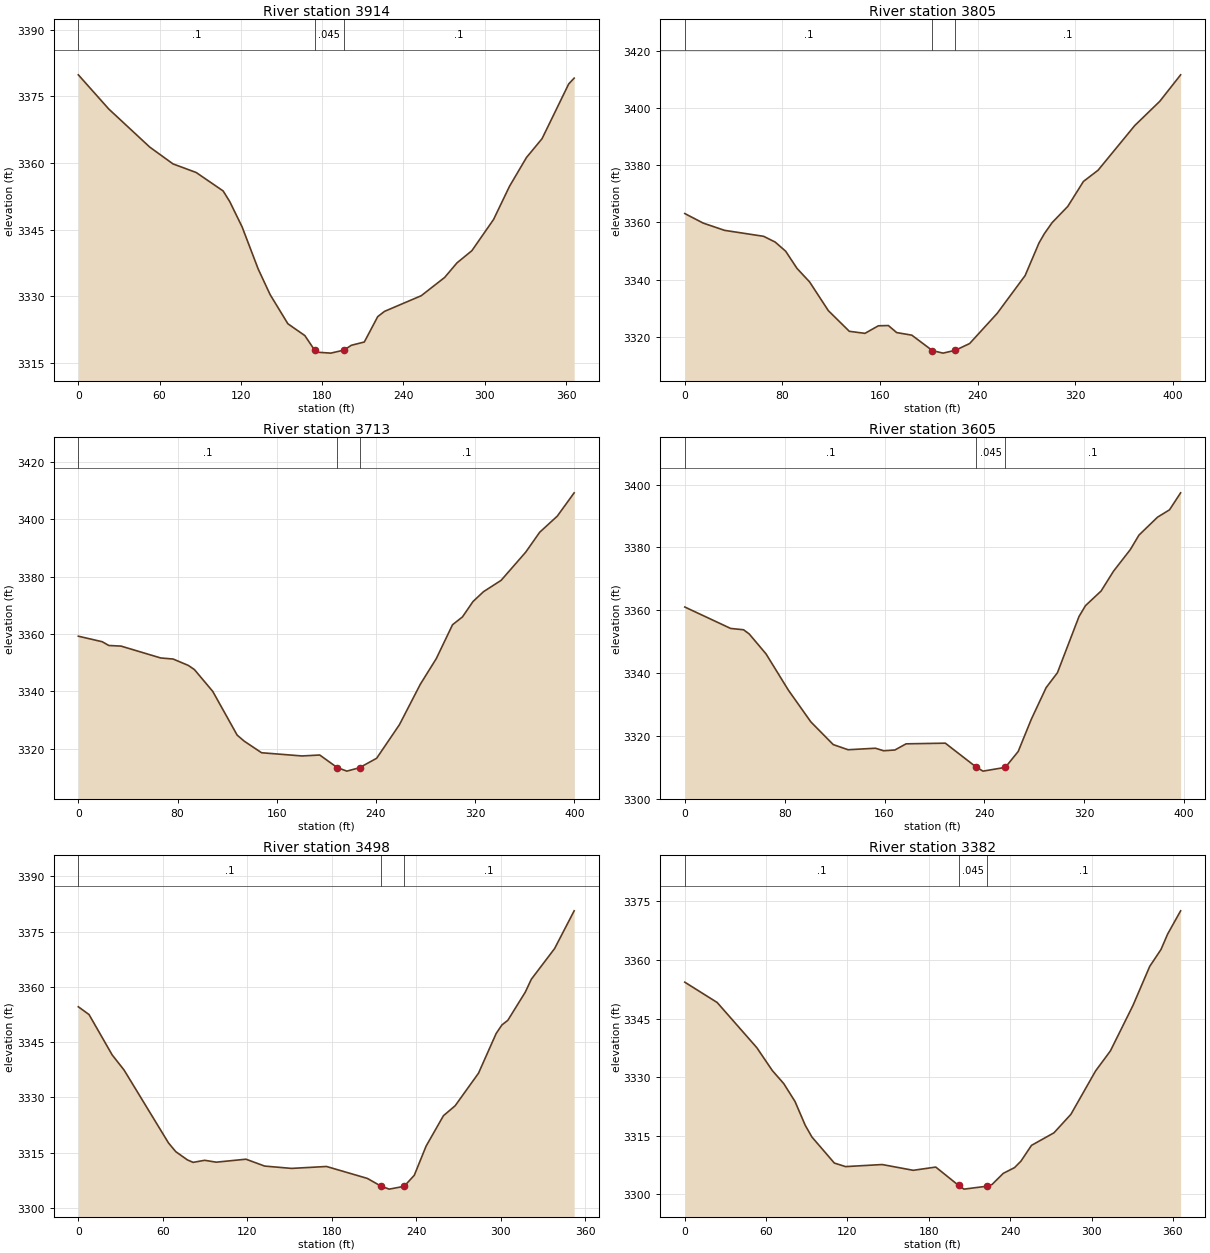
Type RM Length L Ch R = 1 ,3914    ,108.5,108.7,108.6
XS GIS Cut Line= 3
2227426.32178343597196.7020187372227236.05172528597057.010077315
2227128.87428747596983.551383981
#Sta/Elev= 30
       0 3379.85    22.5 3372.15    52.7  3363.6    69.9 3359.81      87 3357.88
   106.9 3353.73   111.8 3351.32   120.9 3345.64   132.8 3336.15   141.6  3330.4
   154.7 3323.85   167.2  3321.2  174.36 3317.95   176.3 3317.46   186.3 3317.25
   196.13317.927   201.5 3319.01   211.1 3319.75     221 3325.46     226 3326.64
   253.1 3330.16   270.4 3334.27   279.5 3337.55   290.5 3340.29   306.5 3347.31
   318.3 3354.79   330.8 3361.25   342.3 3365.49     362 3377.81     366  3379.1
#Mann= 3 ,0,0
       0      .1       0  174.36    .045       0   196.1      .1       0
Bank Sta=174.36,196.1
XS Rating Curve= 0 ,0
Exp/Cntr(USF)=0,0
Exp/Cntr=0.3,0.1

Type RM Length L Ch R = 1 ,3805    ,90.9,92.8,94
XS GIS Cut Line= 2
2227487.98506039597121.5606056182227170.80944498596867.328785482
#Sta/Elev= 30
       0 3363.09    15.1 3359.75    32.6 3357.22    64.6 3355.14    74.1 3353.13
    82.7 3349.93      92 3343.92   102.3 3339.21   117.7 3329.16   134.9 3321.94
   147.7 3321.23   158.7 3323.87   166.9 3323.96   173.7  3321.5   186.1  3320.6
     203 3315.21   211.7 3314.32   221.83315.315   233.5 3317.66   256.1 3328.21
     279 3341.41   290.4 3352.82   294.8 3356.07   301.2 3359.94     314 3365.59
   326.8  3374.3   338.8 3378.22   368.9 3393.84   389.4  3402.3   406.5 3411.56
#Mann= 3 ,-1,0
       0      .1       0     203    .045       0   221.8      .1       0
Bank Sta=203,221.8
XS Rating Curve= 0 ,0
Exp/Cntr(USF)=0,0
Exp/Cntr=0.3,0.1

Type RM Length L Ch R = 1 ,3713    ,104.5,107.6,109.7
XS GIS Cut Line= 3
2227514.95985864597093.181905059 2227419.8099624596960.864080595
2227262.21794675596783.944742268
#Sta/Elev= 30
       0 3359.24    19.2 3357.32    24.6    3356    34.5 3355.78    66.4 3351.65
    76.5 3351.27    88.7 3349.05    93.6 3347.61   108.4    3340   128.1 3324.74
   133.8 3322.63   147.8 3318.59   180.5 3317.47   194.7  3317.8   208.8 3313.42
   216.6 3312.18   226.8 3313.38   240.6 3316.67     259 3328.39   275.8 3342.46
   288.7 3351.42   301.8 3363.23   309.8 3365.96   318.3 3371.32   326.8 3374.77
     341 3378.72   360.8 3388.53   372.1 3395.49   386.3 3401.12   399.9 3409.24
#Mann= 3 ,0,0
       0      .1       0   208.8    .045       0   226.8      .1       0
Bank Sta=208.8,226.8
XS Rating Curve= 0 ,0
Exp/Cntr(USF)=0,0
Exp/Cntr=0.3,0.1

Type RM Length L Ch R = 1 ,3605    ,105.5,106.9,109.1
XS GIS Cut Line= 2
 2227583.5648767597079.1604273072227403.22793372596725.228362312
#Sta/Elev= 30
       0 3361.05    36.7 3354.23    47.1  3353.8    51.6 3352.47    65.1 3346.11
      83 3334.57     101 3324.47   118.9 3317.25   130.8 3315.61   152.7 3316.09
   159.3 3315.29   168.3 3315.53   177.3 3317.49   208.7  3317.7   233.5 3310.07
   238.9  3308.8   256.8    3310   267.1 3315.07   277.6 3325.33   289.5 3335.41
   298.5 3340.12   315.8 3358.03     321 3361.49   333.5 3366.14   343.4 3372.43
   356.9 3379.33   363.8 3383.93   378.7 3389.65   388.3 3391.99   397.2  3397.4
#Mann= 3 ,-1,0
       0      .1       0   233.5    .045       0   256.8      .1       0
Bank Sta=233.5,256.8
XS Rating Curve= 0 ,0
Exp/Cntr(USF)=0,0
Exp/Cntr=0.3,0.1

Type RM Length L Ch R = 1 ,3498    ,117,116.1,116.1
XS GIS Cut Line= 3
2227623.81728682597036.5379824512227587.69006059596882.395150537
2227535.90770299596695.737815016
#Sta/Elev= 30
       0  3354.6     7.6 3352.49      24 3341.54    32.5  3337.4      64 3317.62
    69.2 3315.24    77.4 3313.02    81.5 3312.34    89.7  3312.9    97.9 3312.39
     119  3313.2   132.3 3311.33   151.4  3310.7   176.2 3311.22   205.2 3307.98
  215.09 3305.83   220.7 3305.07   231.3 3305.83   238.5 3308.83   246.9 3316.76
   259.2 3325.01   267.5 3327.71   284.1 3336.56   296.6 3347.32   300.7 3349.66
   304.9 3350.92   317.3 3358.57   321.6 3362.08   338.1  3370.4     352 3380.66
#Mann= 3 ,0,0
       0      .1       0  215.09    .045       0   231.3      .1       0
Bank Sta=215.09,231.3
XS Rating Curve= 0 ,0
Exp/Cntr(USF)=0,0
Exp/Cntr=0.3,0.1

Type RM Length L Ch R = 1 ,3382    ,161.7,162.6,163.4
XS GIS Cut Line= 2
2227743.40903214597011.4327086552227644.89008621596659.300634595
#Sta/Elev= 30
       0 3354.31    23.9  3349.1    53.1 3337.54    64.6 3331.65      73 3328.32
    81.3 3323.74    88.8 3317.67    93.7 3314.67   110.3 3307.97   118.6 3307.06
   145.6 3307.59   168.5 3306.11   185.1 3306.94   201.93302.253   205.9 3301.29
   223.23302.053   226.6 3302.48   234.9 3305.33   243.2  3306.8   247.9 3308.45
   255.7  3312.5   272.3 3315.72   284.8 3320.47     303 3331.58   313.9  3336.7
   330.5 3348.31   342.9 3358.35   351.2 3362.67   356.1 3366.62   365.7 3372.59
#Mann= 3 ,-1,0
       0      .1       0   201.9    .045       0   223.2      .1       0
Bank Sta=201.9,223.2
XS Rating Curve= 0 ,0
Exp/Cntr(USF)=0,0
Exp/Cntr=0.3,0.1

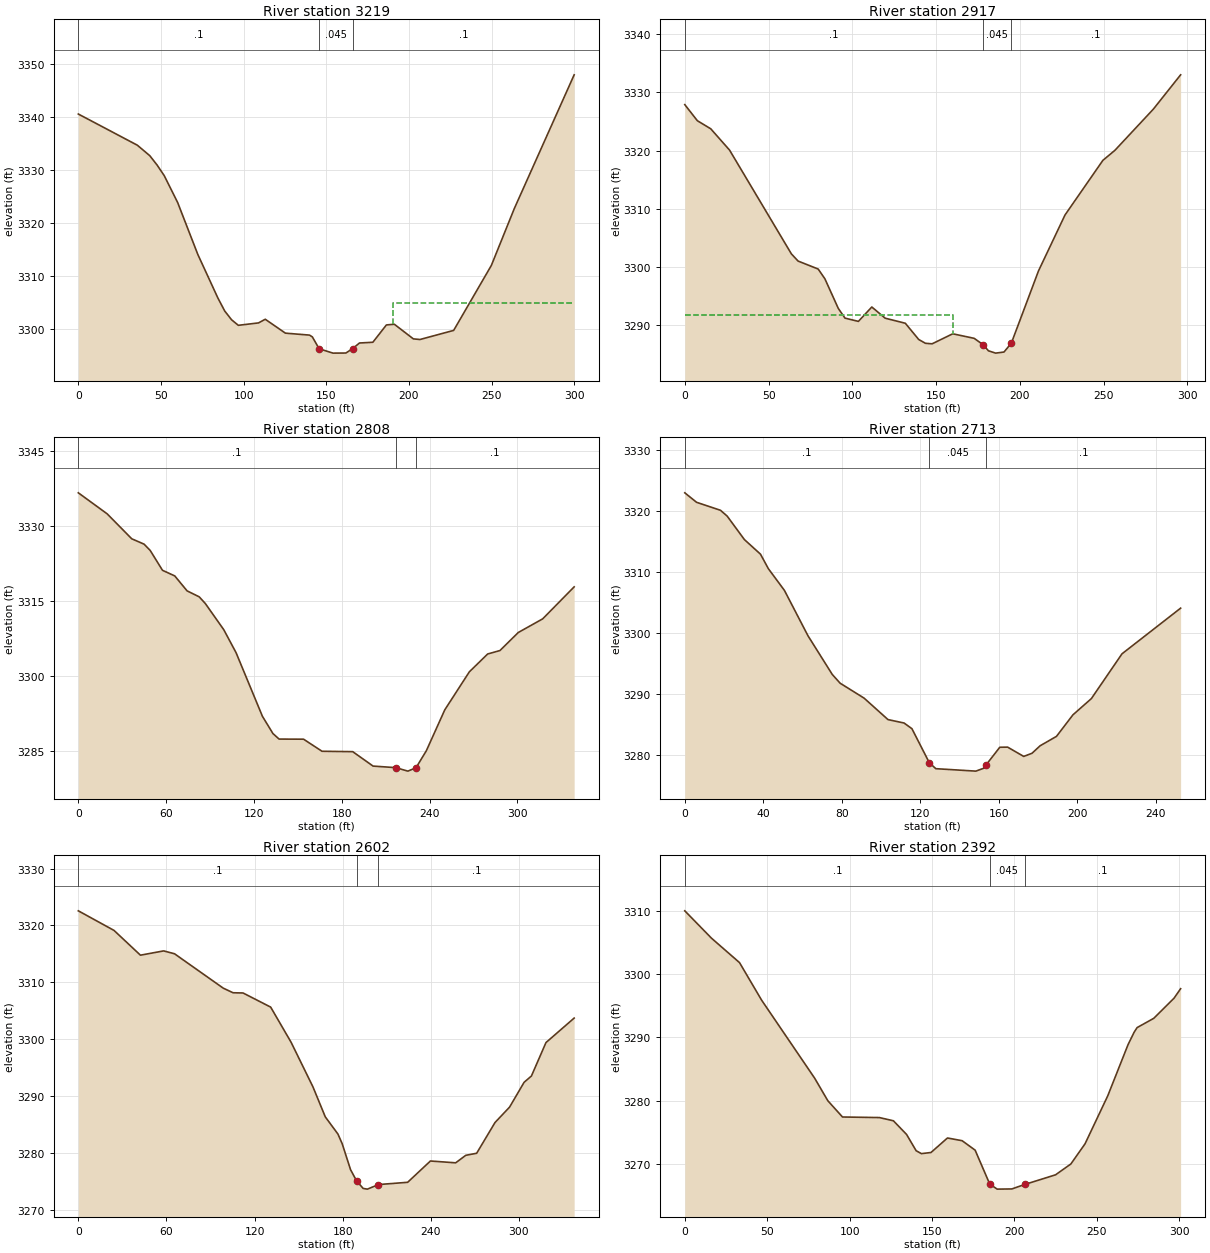
Type RM Length L Ch R = 1 ,3219    ,302.3,302,299.2
XS GIS Cut Line= 2
2227872.93558007596920.2009767042227816.36034379596625.619574027
#Sta/Elev= 30
       0 3340.56    35.7 3334.68    43.2 3332.71    47.7 3330.92      52 3328.92
    60.1 3323.86    72.3 3314.06    84.5  3305.8    88.6 3303.38    92.7 3301.74
    96.8 3300.69     109 3301.14   113.1 3301.83   125.3 3299.21   139.9 3298.84
   141.6  3298.5   145.73296.262   154.1 3295.44   161.9 3295.46     166  3296.3
   170.1 3297.35   178.2 3297.49   186.4 3300.76   191.2 3300.89   202.7 3298.13
   206.7 3298.01   227.1 3299.73   249.9 3311.99   263.8 3322.73     300 3347.96
#Mann= 3 ,-1,0
       0      .1       0   145.7    .045       0     166      .1       0
#XS Ineff= 2 , 0
                          190.64         3304.92
Permanent Ineff=
       F       F
Bank Sta=145.7,166
XS Rating Curve= 0 ,0
Exp/Cntr(USF)=0,0
Exp/Cntr=0.3,0.1

Type RM Length L Ch R = 1 ,2917    ,104.3,109.4,114.9
XS GIS Cut Line= 4
2228102.92361376596876.7241168832228105.29392107596721.864039105
2228080.01064307596653.915229468 2228055.5174675596589.916932019
#Sta/Elev= 30
       0 3327.89     7.5 3325.13    15.5 3323.74    26.7 3320.09    63.6 3302.27
    67.6 3301.03    79.6 3299.66    83.6 3297.99    91.6  3292.9    95.6 3291.23
   103.6 3290.67   111.6 3293.14   119.6 3291.22   131.6 3290.35   139.6 3287.56
   143.6 3286.91   147.6 3286.82   159.9 3288.54   172.7 3287.76   178.1 3286.65
   181.2 3285.62   185.5 3285.22   190.5 3285.41   194.9 3286.95   211.1 3299.35
   226.9 3308.94   249.5 3318.32   256.7 3320.05   279.6 3327.11   295.9 3333.01
#Mann= 3 ,-1,0
       0      .1       0   178.1    .045       0   194.9      .1       0
#XS Ineff= 2 , 0
          159.85 3291.82
Permanent Ineff=
       F       F
Bank Sta=178.1,194.9
XS Rating Curve= 0 ,0
Exp/Cntr(USF)=0,0
Exp/Cntr=0.3,0.1

Type RM Length L Ch R = 1 ,2808    ,97.6,95.3,91.5
XS GIS Cut Line= 3
2228134.38278057596916.0062830272228220.64887697596642.063692903
2228206.40818641596592.517800706
#Sta/Elev= 30
       0 3336.68    19.7 3332.47    36.5 3327.47    44.9  3326.4    49.1 3325.14
    57.5 3321.16    65.9 3320.03    74.3 3317.04    82.6 3315.84    86.8 3314.49
    99.4 3309.25   107.8 3304.64   125.8  3291.9     133 3288.44   137.2 3287.34
   153.9 3287.32   166.5  3284.9   187.5 3284.82   201.4 3281.93   216.8 3281.62
   225.2 3280.92  230.75  3281.6   237.8    3285   250.4  3293.2   267.2 3300.82
   279.7 3304.39   288.1 3305.08   300.6 3308.69   317.3 3311.43   338.8 3317.84
#Mann= 3 ,0,0
       0      .1       0   216.8    .045       0  230.75      .1       0
Bank Sta=216.8,230.75
XS Rating Curve= 0 ,0
Exp/Cntr(USF)=0,0
Exp/Cntr=0.3,0.1

Type RM Length L Ch R = 1 ,2713    ,119.6,111.1,102.5
XS GIS Cut Line= 3
2228260.94410129596879.0944241962228291.75809636596711.592707416
2228268.05502323596632.582463651
#Sta/Elev= 30
       0 3322.99       6 3321.44    18.2 3320.13    21.6 3319.18    30.4 3315.33
    38.6 3312.94    42.6 3310.57    50.8 3307.01    62.8 3299.58    75.2 3293.24
    79.2 3291.81    91.4 3289.37   103.6 3285.85   111.8 3285.29   115.8 3284.36
   124.7 3278.77     128 3277.81   148.4 3277.41   152.4 3277.88   153.73278.465
   160.6 3281.32   164.6 3281.34   172.8 3279.82     177 3280.33   181.2 3281.57
   189.5  3283.1   197.9 3286.63   207.3 3289.29   222.9 3296.62   252.8  3304.1
#Mann= 3 ,-1,0
       0      .1       0   124.7    .045       0   153.7      .1       0
Bank Sta=124.7,153.7
XS Rating Curve= 0 ,0
Exp/Cntr(USF)=0,0
Exp/Cntr=0.3,0.1

Type RM Length L Ch R = 1 ,2602    ,213.2,209.1,205.2
XS GIS Cut Line= 2
2228506.52294508596882.0050622912228306.77004267 596609.66949296
#Sta/Elev= 30
       0 3322.57    24.3 3319.13    42.3 3314.78    58.1 3315.53    65.5 3315.03
    98.7 3308.99   105.4 3308.18   112.2 3308.14     131 3305.66   144.9 3299.49
   159.8 3291.65   168.2 3286.38   176.8 3283.37   179.7 3281.68   185.4 3277.11
   189.5 3275.15     194 3273.81   196.9 3273.69   204.4 3274.49   224.3 3274.89
   239.8 3278.63     257 3278.31   263.9 3279.63   271.3 3279.99   283.8 3285.39
   293.7 3288.09   303.6 3292.45   308.6 3293.56   318.5 3299.43   337.7 3303.73
#Mann= 3 ,-1,0
       0      .1       0   189.5    .045       0   204.4      .1       0
Bank Sta=189.5,204.4
XS Rating Curve= 0 ,0
Exp/Cntr(USF)=0,0
Exp/Cntr=0.3,0.1

Type RM Length L Ch R = 1 ,2392    ,100.9,99.5,96
XS GIS Cut Line= 2
2228685.84407159596641.252109373 2228416.5942815596506.956176066
#Sta/Elev= 30
       0 3310.09    16.2 3305.75    33.2 3301.88    46.6 3295.93    78.8 3283.55
    86.8 3279.97    95.7 3277.39   118.1  3277.3   126.6 3276.79   134.6 3274.62
   140.4 3272.04   143.6 3271.58   149.4 3271.76   159.4 3274.06   168.3 3273.63
   176.2 3272.13   185.1 3266.73   189.6 3265.95   198.5 3265.98   206.3 3266.69
     225 3268.22   234.3 3269.94   242.9 3273.14   256.7 3280.76     269 3288.87
   272.7 3290.84   274.5 3291.57   284.6 3293.04   296.9 3296.23   300.9 3297.74
#Mann= 3 ,-1,0
       0      .1       0   185.1    .045       0   206.3      .1       0
Bank Sta=185.1,206.3
XS Rating Curve= 0 ,0
Exp/Cntr(USF)=0,0
Exp/Cntr=0.3,0.1

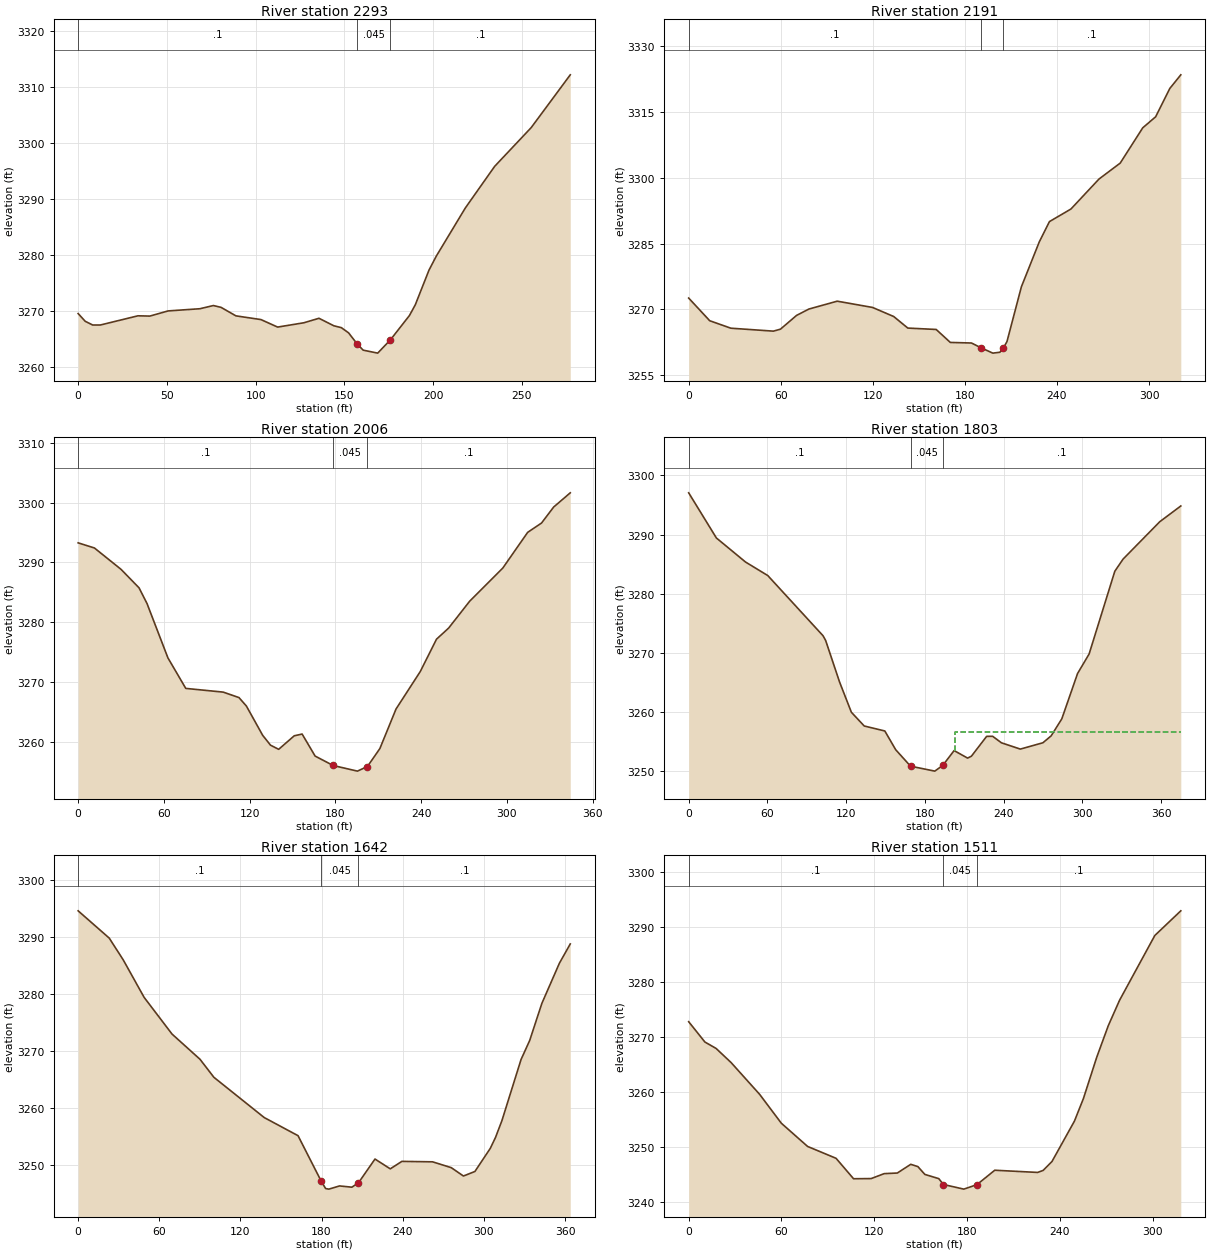
Type RM Length L Ch R = 1 ,2293    ,100.1,102.3,104.4
XS GIS Cut Line= 3
2228683.94184719596513.025599419 2228548.7465412596464.741561563
2228418.81858478596433.137464057
#Sta/Elev= 30
       0 3269.59       4 3268.21     8.2 3267.55    12.5 3267.55    33.7 3269.19
    40.4 3269.14    50.7 3270.06    68.6 3270.45    76.2 3271.02    80.5  3270.7
    88.9 3269.18     103 3268.52   112.4 3267.18   127.2 3267.95   135.7 3268.75
   144.1 3267.41   148.3 3267.08   152.4 3266.15   157.23264.187   160.6 3263.07
   168.8 3262.54     1763264.923   186.7 3269.25     190 3271.17   197.7 3277.33
   201.8 3279.82   218.2 3288.42   234.7 3295.82   255.3 3302.73   277.3 3312.13
#Mann= 3 ,-1,0
       0      .1       0   157.2    .045       0     176      .1       0
Bank Sta=157.2,176
XS Rating Curve= 0 ,0
Exp/Cntr(USF)=0,0
Exp/Cntr=0.3,0.1

Type RM Length L Ch R = 1 ,2191    ,182.7,184.6,186.2
XS GIS Cut Line= 2
2228728.04379727596461.2971530012228449.92592945596301.639944406
#Sta/Elev= 30
       0 3272.55    13.7 3267.38    27.5 3265.67    55.2    3265    59.8 3265.45
    70.3 3268.59    78.3 3270.04    96.8 3271.84   119.8 3270.41   133.6 3268.34
   142.8  3265.7   161.3 3265.38   170.5 3262.42   184.3 3262.29   190.5  3261.2
   198.2 3259.98   202.8 3260.18   205.1 3261.18   205.1 3261.19   207.4 3262.59
   216.8 3275.11   228.5  3285.4   235.1 3290.01   249.1 3292.88   267.4 3299.73
   281.2 3303.36   295.9 3311.42   304.3 3313.94   313.5 3320.39   320.7 3323.52
#Mann= 3 ,-1,0
       0      .1       0   190.5    .045       0   205.1      .1       0
Bank Sta=190.5,205.1
XS Rating Curve= 0 ,0
Exp/Cntr(USF)=0,0
Exp/Cntr=0.3,0.1

Type RM Length L Ch R = 1 ,2006    ,203.9,203.5,200.2
XS GIS Cut Line= 3
2228816.12197481596359.6552090722228773.20283005596315.760629203
2228568.36145733596120.673607563
#Sta/Elev= 30
       0 3293.28    11.4 3292.42      30 3288.86    42.6 3285.77    48.2 3283.14
    62.8 3274.08    75.3 3268.98   101.5 3268.36   112.5 3267.45   117.7 3266.04
   129.1 3261.15   134.6  3259.5   140.3 3258.81   151.2 3261.07   156.7 3261.36
   165.8 3257.68   178.43256.111   195.4 3255.17   202.43255.941   211.1 3258.94
   222.4 3265.54   239.4 3271.81   250.7 3277.19   259.2 3279.05   273.9 3283.53
   297.1 3289.07   314.5 3295.03   324.2 3296.59   332.7 3299.26   344.3 3301.63
#Mann= 3 ,-1,0
       0      .1       0   178.4    .045       0   202.4      .1       0
Bank Sta=178.4,202.4
XS Rating Curve= 0 ,0
Exp/Cntr(USF)=0,0
Exp/Cntr=0.3,0.1

Type RM Length L Ch R = 1 ,1803    ,159.5,160.6,161.2
XS GIS Cut Line= 2
  2228973.395833 596196.299934472228667.10920902 595979.75334045
#Sta/Elev= 30
       0 3297.04    21.1 3289.42    43.3 3285.36    60.3 3283.07   102.4 3272.91
   104.4 3272.11     115  3265.1     124 3259.99   133.8 3257.67   149.5 3256.83
   157.8 3253.66   169.13250.887   187.6 3250.05   193.73251.023   202.3 3253.52
   212.6 3252.25   215.5 3252.57   227.1 3255.92   231.7 3255.93   238.4 3254.83
   252.8 3253.77     270 3254.84   276.3 3256.01   284.4 3258.88   296.4 3266.53
   305.2 3269.82   324.8  3283.8   331.1 3285.85   359.1 3292.17   375.1 3294.82
#Mann= 3 ,-1,0
       0      .1       0   169.1    .045       0   193.7      .1       0
#XS Ineff= 2 , 0
                          202.94         3256.61
Permanent Ineff=
       F       F
Bank Sta=169.1,193.7
XS Rating Curve= 0 ,0
Exp/Cntr(USF)=0,0
Exp/Cntr=0.3,0.1

Type RM Length L Ch R = 1 ,1642    ,133.3,130.6,127.1
XS GIS Cut Line= 2
2229069.99714576 596088.144171372228787.93057552595858.224362016
#Sta/Elev= 30
       0  3294.6      23 3289.81    33.3 3286.01    48.8 3279.41    69.4 3272.98
    90.1 3268.55   100.4 3265.38   137.6 3258.32   162.6 3255.14   179.7 3247.17
     183 3245.86   185.4 3245.76   193.3 3246.32   202.4  3246.1   207.3 3246.87
   219.5 3251.04   230.8 3249.32   239.4 3250.63   262.1 3250.55   275.9 3249.53
   284.9 3248.06   293.4 3248.86   304.8 3252.93   308.6 3254.82   313.3 3257.74
   327.5  3268.5   333.9 3271.85   342.9 3278.36   355.9 3285.42   363.9 3288.79
#Mann= 3 ,-1,0
       0      .1       0   179.7    .045       0   207.3      .1       0
Bank Sta=179.7,207.3
XS Rating Curve= 0 ,0
Exp/Cntr(USF)=0,0
Exp/Cntr=0.3,0.1

Type RM Length L Ch R = 1 ,1511    ,200,209.4,212.3
XS GIS Cut Line= 4
2229098.44083352595961.7277813472229000.61023175595863.523100815
2228932.32977417595827.4320018122228846.60299728595771.605724408
#Sta/Elev= 30
       0 3272.77    10.5 3269.07    17.7 3267.91    27.4 3265.34    45.9 3259.54
    59.9 3254.29    76.9 3250.06    95.3  3247.9   106.6 3244.18     118 3244.21
   126.4 3245.11   134.9 3245.22   143.6 3246.81   148.2 3246.39   152.7 3244.97
   161.7  3244.2  164.75 3243.13   177.9 3242.29   186.4 3243.11   197.9 3245.73
   225.6 3245.33   229.2  3245.7   234.9 3247.32   249.4 3254.66   255.2 3258.76
   263.8 3266.27   271.3 3272.04   278.6 3276.68   301.4 3288.47   318.2 3292.96
#Mann= 3 ,0,0
       0      .1       0  164.75    .045       0   186.4      .1       0
Bank Sta=164.75,186.4
XS Rating Curve= 0 ,0
Exp/Cntr(USF)=0,0
Exp/Cntr=0.3,0.1

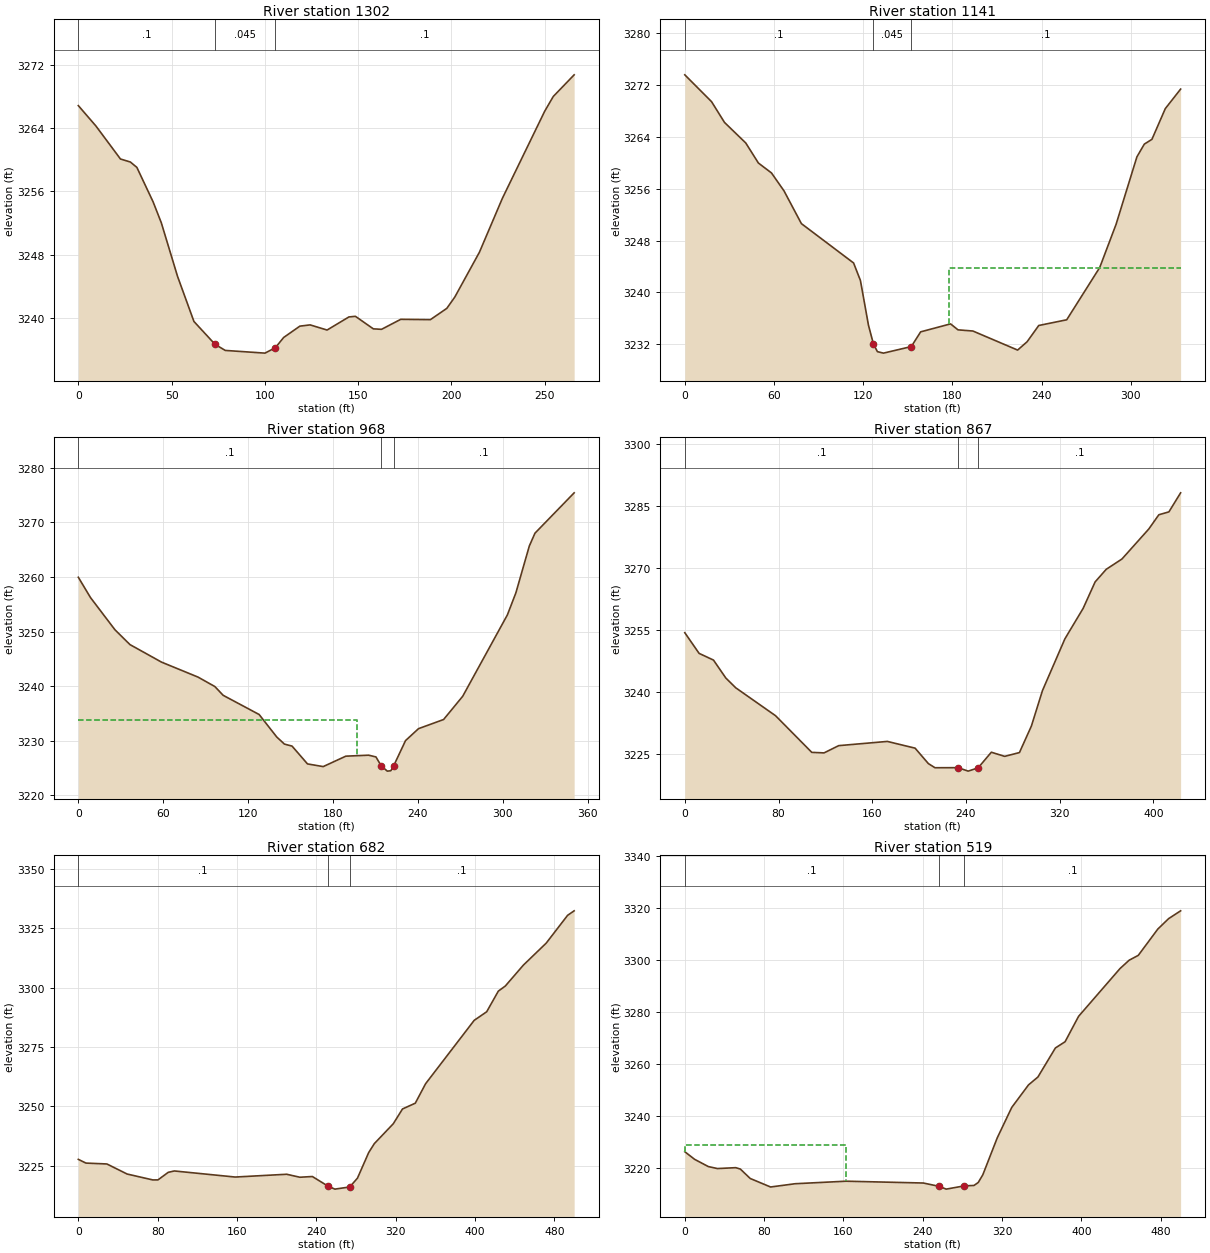
Type RM Length L Ch R = 1 ,1302    ,167.8,161.3,153.7
XS GIS Cut Line= 2
2229191.46749452595869.8792508632229083.95035481595626.685720556
#Sta/Elev= 30
       0 3266.82     9.5 3264.23    22.6 3260.09    27.9 3259.71    31.4 3259.03
    40.1 3254.69    44.5 3252.05    53.2  3245.3      62 3239.61    73.3 3236.73
    78.8 3235.96   100.1 3235.62   105.7 3236.31   110.1 3237.59   118.8 3239.02
   124.3 3239.18   133.4 3238.53   145.1 3240.18   148.6 3240.26   158.2 3238.68
   162.6 3238.62   172.9 3239.88   188.8 3239.84   197.6 3241.26   201.9 3242.69
   215.1 3248.34   227.4 3255.13   250.1 3266.11   254.7 3267.97   265.9  3270.7
#Mann= 3 ,-1,0
       0      .1       0    73.3    .045       0   105.7      .1       0
Bank Sta=73.3,105.7
XS Rating Curve= 0 ,0
Exp/Cntr(USF)=0,0
Exp/Cntr=0.3,0.1

Type RM Length L Ch R = 1 ,1141    ,172.9,173.1,167.6
XS GIS Cut Line= 2
2229398.72169269595784.0056939432229132.72053868595582.968518143
#Sta/Elev= 30
       0 3273.56      18 3269.42    26.7 3266.22      41 3263.05    49.5 3259.96
    58.3 3258.43    66.7 3255.67    78.4 3250.62   113.5 3244.55   118.1 3241.85
   123.5 3234.96   126.83232.092   129.5 3230.88   133.6 3230.65   152.3 3231.66
   158.6 3233.93   178.7 3235.16   183.7 3234.24   193.7 3234.06   223.8 3231.12
   230.2 3232.41     238 3234.91   256.8 3235.79     279 3243.85     290 3250.51
     304 3260.91     309 3262.88   314.1 3263.61   323.1 3268.35   333.4 3271.36
#Mann= 3 ,-1,0
       0      .1       0   126.8    .045       0   152.3      .1       0
#XS Ineff= 2 , 0
                          177.82         3243.72
Permanent Ineff=
       F       F
Bank Sta=126.8,152.3
XS Rating Curve= 0 ,0
Exp/Cntr(USF)=0,0
Exp/Cntr=0.3,0.1

Type RM Length L Ch R = 1 ,968     ,101.3,101,99.3
XS GIS Cut Line= 5
2229482.58798399595703.3723660592229443.57057966595663.271144944
2229346.02706884595557.0570998292229279.91424484595477.938474386
2229244.08683204595447.084771723
#Sta/Elev= 30
       0 3259.95     8.6 3256.23    25.9 3250.33    36.5 3247.62    58.8 3244.41
    84.6 3241.67    96.5 3239.94   102.4 3238.33   127.8 3234.82   140.3 3230.69
   145.7  3229.4   151.1 3229.03     162 3225.77   173.1 3225.28   189.1 3227.19
   205.2 3227.37   210.4 3227.05  214.03 3225.44   218.4 3224.45   220.9 3224.52
  222.94 3225.44   231.3 3230.04   240.5 3232.23   258.2  3233.9   271.7 3238.15
   303.3 3253.06   309.3 3257.09   318.8 3265.67   322.8 3268.02   350.5 3275.41
#Mann= 3 ,0,0
       0      .1       0  214.03    .045       0  222.94      .1       0
#XS Ineff= 2 , 0
          197.27 3233.88
Permanent Ineff=
       F       F
Bank Sta=214.03,222.94
XS Rating Curve= 0 ,0
Exp/Cntr(USF)=0,0
Exp/Cntr=0.3,0.1

Type RM Length L Ch R = 1 ,867     ,182.5,184.4,185.4
XS GIS Cut Line= 4
2229574.76144716595651.8463646922229481.70493784595542.109915019
2229380.74740414595450.8091888922229264.86571329595366.531595543
#Sta/Elev= 30
       0 3254.35    12.2 3249.34    24.5 3247.71      35 3243.37    43.5 3240.99
    77.5 3234.22   108.4 3225.34   118.9 3225.21   131.4 3226.97   172.9 3227.99
   196.6 3226.36   207.9 3222.63   213.6 3221.61   233.4 3221.63   241.9 3220.79
   250.4 3221.58   261.7 3225.37   273.1 3224.37   285.7 3225.29   295.9 3231.72
   305.4 3240.35   324.5 3252.86   340.1 3260.26   350.3 3266.66   359.8 3269.72
   373.2 3272.21   396.1 3279.48   404.7 3282.94   413.3 3283.64   423.3 3288.26
#Mann= 3 ,-1,0
       0      .1       0   233.4    .045       0   250.4      .1       0
Bank Sta=233.4,250.4
XS Rating Curve= 0 ,0
Exp/Cntr(USF)=0,0
Exp/Cntr=0.3,0.1

Type RM Length L Ch R = 1 ,682     ,160.5,162.9,164.9
XS GIS Cut Line= 2
2229698.53707176595547.0854272892229379.96499998595161.713094236
#Sta/Elev= 30
       0 3227.74     7.7 3226.18    28.8 3225.81    49.2 3221.58    75.1  3219.1
    80.3 3219.11    90.7  3222.3    96.8 3222.87   158.2 3220.31   210.1 3221.48
   223.4 3220.23     236 3220.53   251.6 3216.53   258.7 3215.23   273.7 3216.14
   281.5 3219.86   292.8  3230.6   298.5 3234.37   317.6 3242.72   326.9 3248.94
   339.8 3251.37   350.2 3259.56   399.2 3286.21   411.8 3289.81   423.5 3298.47
   430.6 3300.65   448.8 3309.43   471.8 3318.67   493.4 3330.37     500 3332.26
#Mann= 3 ,-1,0
       0      .1       0   251.6    .045       0   273.7      .1       0
Bank Sta=251.6,273.7
XS Rating Curve= 0 ,0
Exp/Cntr(USF)=0,0
Exp/Cntr=0.3,0.1

Type RM Length L Ch R = 1 ,519     ,177.9,184.4,193.4
XS GIS Cut Line= 2
 2229789.7517599595473.747799913 2229540.7090152595040.183835412
#Sta/Elev= 30
       0 3226.36     9.9 3223.43    23.7 3220.65    32.9 3219.88    51.4 3220.22
      56 3219.69      66 3216.06    86.5 3212.79   111.4 3214.05   162.7 3215.02
   240.5 3214.32   256.5 3213.04   263.6 3211.97     282 3213.23   291.6 3213.38
   295.9 3214.52   300.5 3217.46   315.1  3231.7   329.7 3243.39   346.6 3252.05
   356.1 3255.09   373.7 3266.25   383.5 3268.66   397.1 3278.42   438.9  3296.8
   448.1 3300.01   457.3 3301.87     477 3311.98   487.9    3316     500    3319
#Mann= 3 ,-1,0
       0      .1       0   256.5    .045       0     282      .1       0
#XS Ineff= 2 , 0
          162.33 3229.12
Permanent Ineff=
       F       F
Bank Sta=256.5,282
XS Rating Curve= 0 ,0
Exp/Cntr(USF)=0,0
Exp/Cntr=0.3,0.1