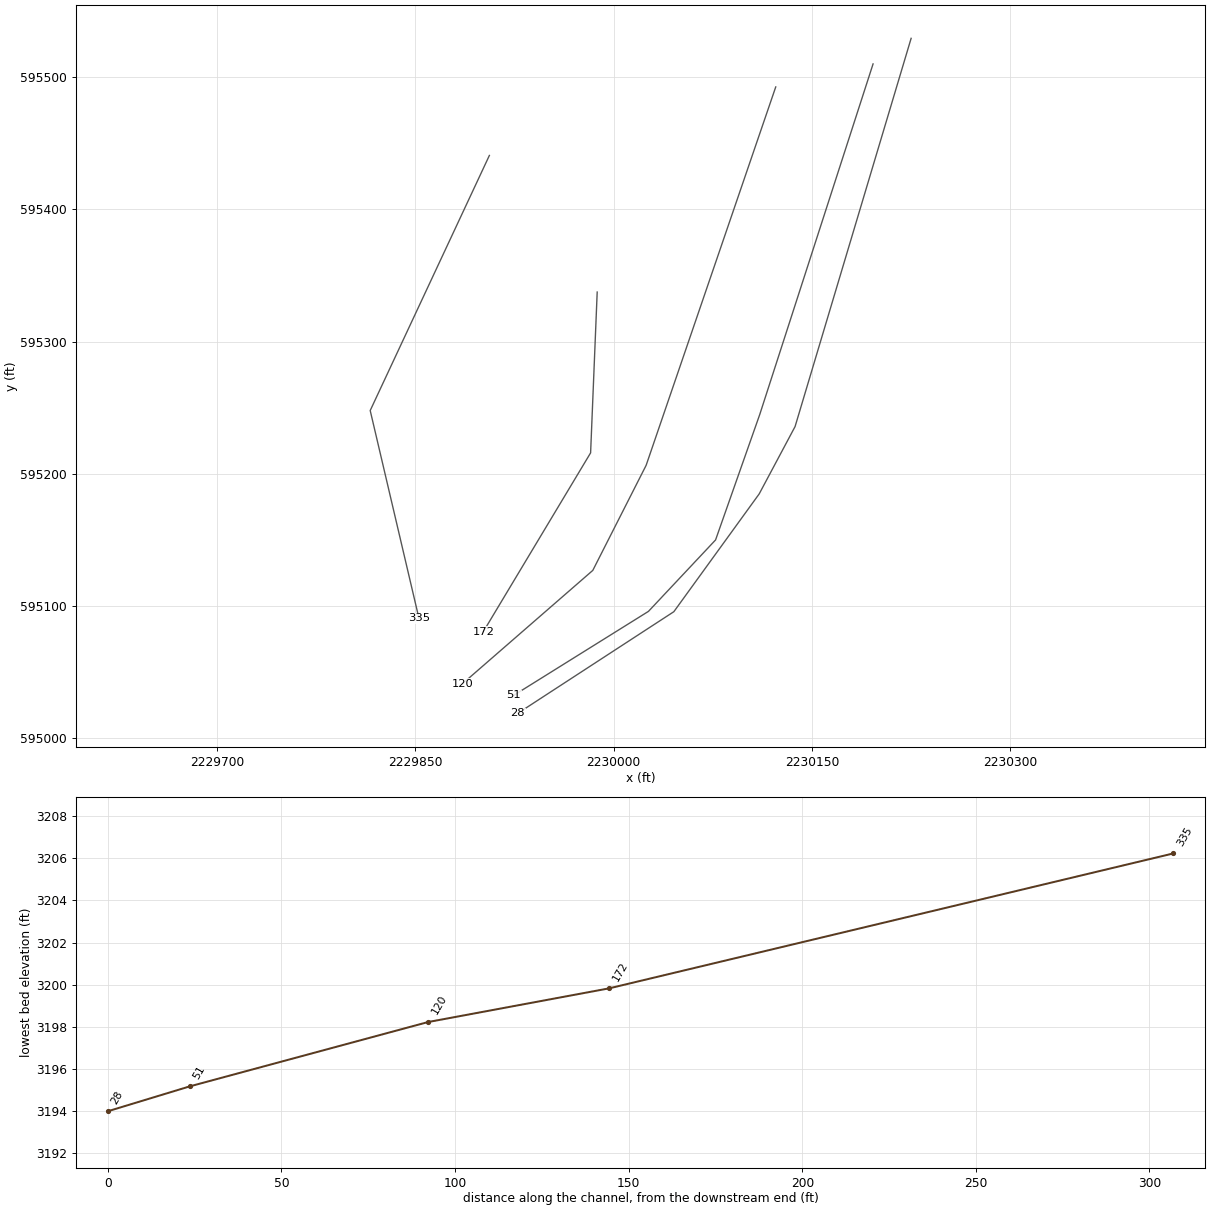
HEC-RAS study POTATOHFK.prj: POTATOHFK

--- POTATOHFK.g01 (geometry) --- (continued)

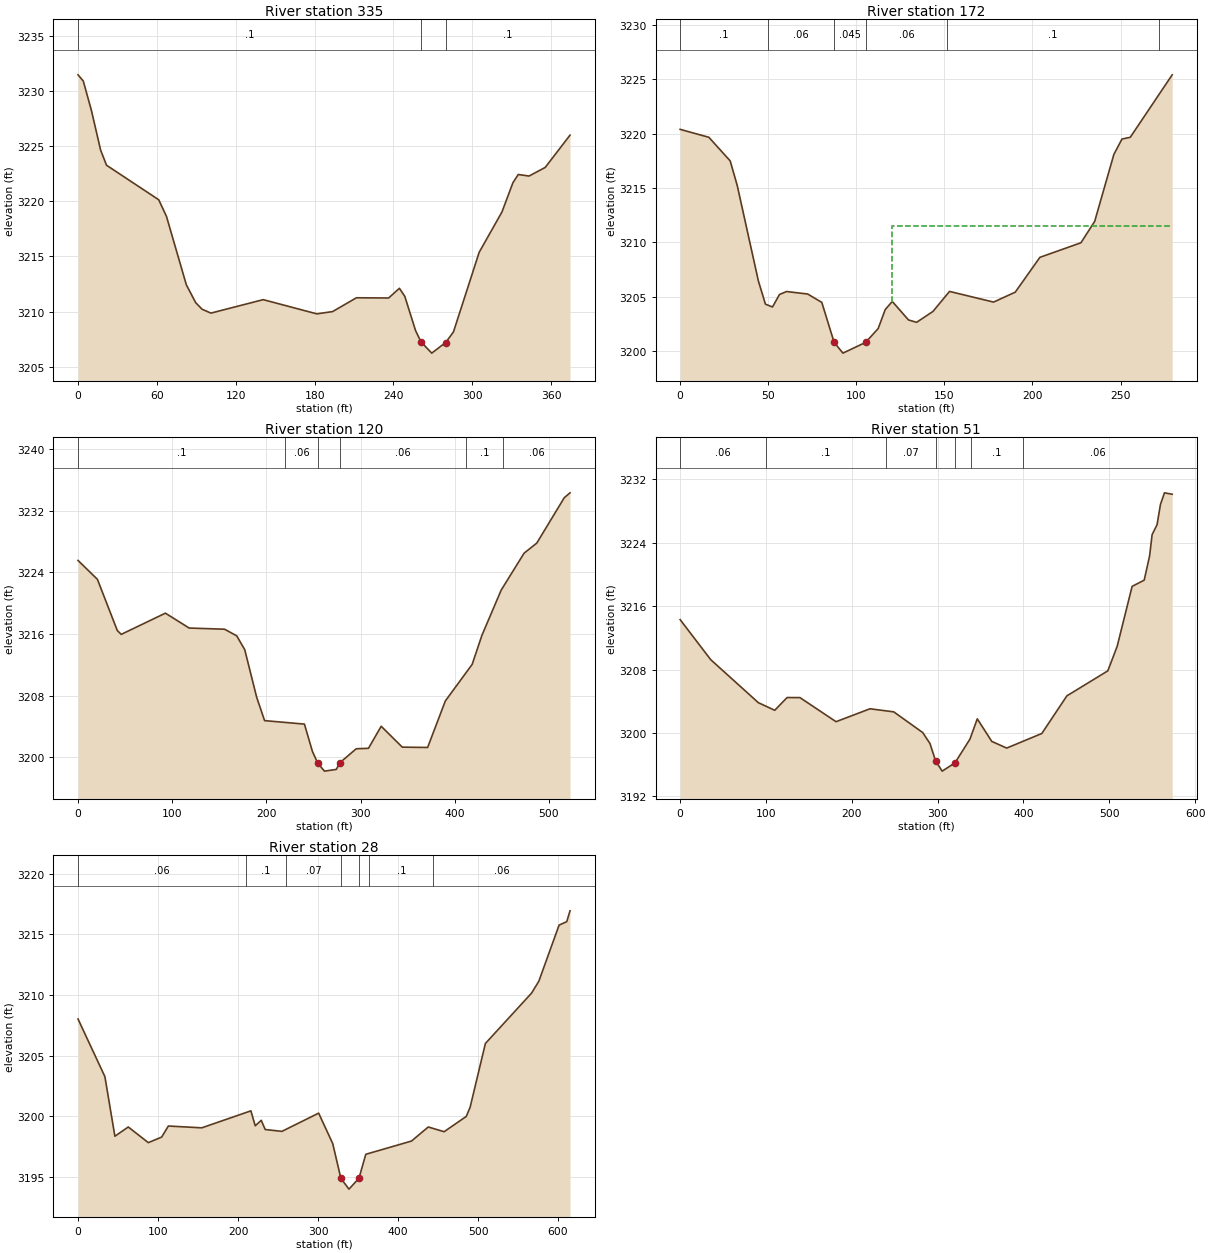
Type RM Length L Ch R = 1 ,335     ,164.9,162.5,160.2
XS GIS Cut Line= 3
2229906.05652671595440.8019830852229815.94199251595247.919890627
 2229852.8134396595090.777294696
#Sta/Elev= 30
       0 3231.47       4 3230.91    10.2 3228.24    17.2 3224.64    21.7 3223.27
    61.4 3220.14    67.3 3218.63    82.4 3212.43    89.5 3210.81    94.4 3210.21
   101.1 3209.86   140.9 3211.08   181.7 3209.79   193.7    3210   211.8 3211.25
   236.3 3211.23   244.5 3212.11   248.6 3211.38   256.8 3208.27   260.9 3207.25
   269.1 3206.23   279.73207.193   285.6 3208.15   305.2 3215.38   322.5 3219.03
   330.8 3221.67   334.9 3222.43   343.1 3222.29   355.4 3223.07   374.3    3226
#Mann= 3 ,-1,0
       0      .1       0   260.9    .045       0   279.7      .1       0
Bank Sta=260.9,279.7
XS Rating Curve= 0 ,0
Exp/Cntr(USF)=0,0
Exp/Cntr=0.3,0.1

Type RM Length L Ch R = 1 ,172     ,56.4,52.2,49.5
XS GIS Cut Line= 3
2229987.58735763 595337.508728142229982.60971227595215.911962987
2229901.54520217 595080.80444615
#Sta/Elev= 30
       0 3220.39    16.3 3219.66    28.4 3217.49    32.4 3215.23    44.4 3206.46
    48.4 3204.33    52.4 3204.07    56.4 3205.22    60.4 3205.49    72.4 3205.26
    80.4 3204.49   87.38 3200.83    92.4 3199.83   105.3 3200.82   112.4 3202.09
   116.4 3203.83   120.4 3204.58   129.6 3202.88   134.2 3202.66   143.5 3203.66
   152.9  3205.5   177.9 3204.52   190.2 3205.43   204.2 3208.63   227.5 3209.97
   235.3 3211.93   246.2 3218.09   250.8  3219.5   255.5 3219.66   279.3  3225.4
#Mann= 6 ,-1,0
       0      .1       0      50     .06       0   87.38    .045       0
   105.3     .06       0   151.7      .1       0   271.7     .06       0
#XS Ineff= 2 , 0
                          120.45          3211.5
Permanent Ineff=
       F       F
Bank Sta=87.38,105.3
XS Rating Curve= 0 ,0
Exp/Cntr(USF)=0,0
Exp/Cntr=0.3,0.1

Type RM Length L Ch R = 1 ,120     ,68.8,68.6,68.6
XS GIS Cut Line= 4
2230122.60435106595492.6220654982230024.60642056595206.513320574
2229984.25982138595127.0346067362229885.50537945595041.174908488
#Sta/Elev= 30
       0 3225.56    20.6 3223.11    41.7 3216.47    45.9 3215.97    92.8 3218.72
     118 3216.79   155.6 3216.64   168.5 3215.78     177 3213.99   189.7 3207.81
   198.1 3204.78   240.4 3204.33   248.9 3200.78   254.4  3199.3   261.6 3198.23
   274.2 3198.45   278.2 3199.34   295.4 3201.13   308.4 3201.19   321.9 3204.05
   344.3 3201.34   371.2  3201.3     390 3207.33   418.5 3212.08   428.8 3215.83
   449.3 3221.71   473.6  3226.5   487.1 3227.81   516.3  3233.7   522.4 3234.33
#Mann= 6 ,-1,0
       0      .1       0     220     .06       0   254.4    .045       0
   278.2     .06       0  411.56      .1       0  451.56     .06       0
Bank Sta=254.4,278.2
XS Rating Curve= 0 ,0
Exp/Cntr(USF)=0,0
Exp/Cntr=0.3,0.1

Type RM Length L Ch R = 1 ,51      ,25,23.6,21.6
XS GIS Cut Line= 5
2230196.19684894595510.0166559052230110.56194232595245.083663555
2230077.11080692595150.0824390252230026.36220376595096.055048921
2229924.48525223595032.539994349
#Sta/Elev= 30
       0  3214.3    35.6 3209.25    91.1 3203.82   110.2 3202.86   124.6 3204.47
   139.6 3204.46   181.6 3201.42   221.2 3203.05   248.9 3202.66   282.6 3200.05
   291.1 3198.66   297.7 3196.45   305.3 3195.18   320.2 3196.22   337.7 3199.23
   346.2 3201.78   363.1 3198.93   380.5 3198.09   421.4 3199.93   450.6 3204.68
   498.3 3207.84   509.2 3210.93   526.6  3218.5   540.7 3219.29     547 3222.36
   549.9 3225.03   555.7 3226.29   559.6 3228.83   564.3 3230.31   573.3 3230.13
#Mann= 7 ,-1,0
       0     .06       0     100      .1       0     240     .07       0
   297.7    .045       0   320.2     .07       0  338.43      .1       0
  399.15     .06       0
Bank Sta=297.7,320.2
XS Rating Curve= 0 ,0
Exp/Cntr(USF)=0,0
Exp/Cntr=0.3,0.1

Type RM Length L Ch R = 1 ,28      ,,,
XS GIS Cut Line= 5
2230224.97955739 595529.367280782230137.22117206595235.795444781
2230110.09835561595184.8892797122230045.54885127595095.800791536
2229927.47243142595018.916996308
#Sta/Elev= 30
       0 3208.02    33.6 3203.27    46.1 3198.36    62.8 3199.12    87.9 3197.83
   104.6 3198.29   112.9  3199.2   154.7 3199.05   216.1 3200.45   221.5 3199.22
     229 3199.67     234 3198.91   254.9 3198.76   300.8 3200.26   318.4 3197.75
  328.55 3194.89   338.7    3194   351.2  3194.9   359.7 3196.87   416.8 3197.96
   437.8 3199.12   457.6 3198.73   485.3 3199.99   490.1 3200.74   509.2    3206
   566.9 3210.15     576 3211.13   601.3 3215.75   610.9 3216.04     615 3216.93
#Mann= 7 ,-1,0
       0     .06       0     210      .1       0     260     .07       0
  328.55    .045       0   351.2     .07       0  364.09      .1       0
  444.09     .06       0
Bank Sta=328.55,351.2
XS Rating Curve= 0 ,0
Exp/Cntr(USF)=0,0
Exp/Cntr=0.3,0.1
LCMann Table=0

Chan Stop Cuts=-1
Use User Specified Reach Order=0
Composite Channel Slope=5